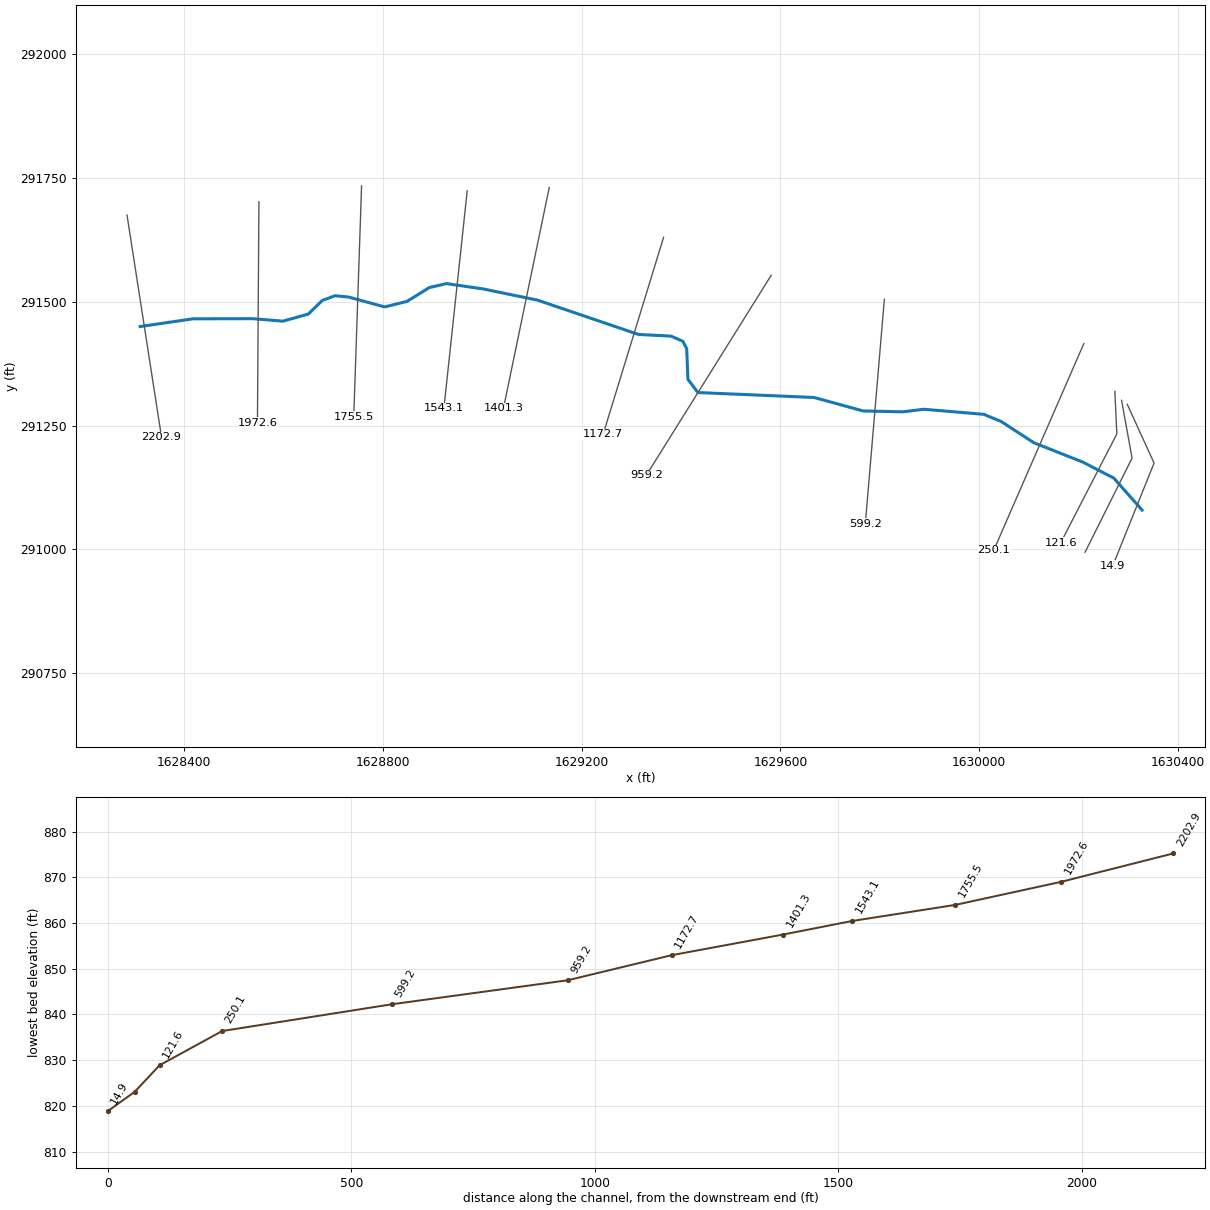
--- lftfrkrffb.prj (project) ---

Proj Title=lftfrkrffb
Current Plan=p01
Default Exp/Contr=0,0
English Units
Geom File=g01
Flow File=f01
Plan File=p01
BEGIN DESCRIPTION:
END DESCRIPTION:
DSS Export Rating Curves= 0
DSS Export Rating Curve Sorted= 0
DSS Export Volume Flow Curves= 0
DXF OffsetX= 0
DXF OffsetY= 0
DXF ScaleX= 0
DXF ScaleY= 0

--- lftfrkrffb.p01 (plan) ---

Plan Title=Approximate Study - 100yr
Program Version=4.00
Geom File=g01
Flow File=f01
Subcritical Flow
K Sum by GR= 0
Std Step Tol= 0.01
Critical Tol= 0.01
Num of Std Step Trials= 20
Max Error Tol= 0.3
Flow Tol Ratio= 0.001
Split Flow NTrial= 30
Split Flow Tol= 0.02
Split Flow Ratio= 0.02
Log Output Level= 0
Friction Slope Method= 1
Unsteady Friction Slope Method= 2
Unsteady Bridges Friction Slope Method= 1
Parabolic Critical Depth
Global Vel Dist= 0 , 0 , 0
Global Log Level= 0
CheckData=True
Encroach Param=-1 ,0,0, 0
Run HTab= 0
Run UNet= 0
Run PostProcess= 0
Run WQNet= 0
UNET Theta= 0
UNET Theta Warmup= 0
UNET ZTol= 0
UNET ZSATol= 0
UNET MxIter= 0
UNET MaxInSteps= 0
UNET DtIC= 0
UNET DtMin= 0
UNET MaxCRTS= 0
UNET WFStab= 0
UNET SFStab= 0
UNET WFX= 1
UNET SFX= 1
UNET DSS MLevel= 1
UNET DZMax Abort= 0
UNET Convert EG Bridges= 0
UNET Use Existing IB Tables= 0
UNET Froude Reduction=False
UNET Froude Limit= 0
UNET Froude Power= 0
UNET Time Slicing=0,0, 5
Write IC File= 0
Echo Input=False
Echo Output=False
Write Detailed= 0
Detailed Automatic Start=False, 0
WQ ULTIMATE=-1
WQ Max Comp Step=1HOUR
WQ Output Interval=15MIN
WQ Output Selected Increments= 0
WQ Output face flow=0
WQ Output face velocity=0
WQ Output face area=0
WQ Output face dispersion=0
WQ Output cell volume=0
WQ Output cell surface area=0
WQ Output cell continuity=0
WQ Output face conc=0
WQ Output face dconc_dx=0
WQ Output face courant=0
WQ Output face peclet=0
WQ Output face adv mass=0
WQ Output face disp mass=0
WQ Output cell mass=0
WQ Output cell source sink temp=0
WQ Output cell source sink nsm=0
WQ Output MaxMinRange=-1
WQ Daily Max Min Mean=-1
WQ Daily Range=0
WQ Daily Time=0
WQ Create Restart=0
WQ Fixed Restart=0
WQ System Summary=False
Sorting and Armoring Iterations= 10
XS Update Threshold= 0.02
Hydraulics Update Threshold= 0.02
Energy Slope Method= 1
Volume Change Method= 0
XS Weighting Method= 0
Number of US Weighted Cross Sections= 1
Number of DS Weighted Cross Sections= 1
Upstream XS Weight=0.25
Main XS Weight=0.5
Downstream XS Weight=0.25
Number of DS XS's Weighted with US Boundary= 1
Upstream Boundary Weight= 1
Weight of XSs Associated with US Boundary= 0
Number of US XS's Weighted with DS Boundary= 1
Downstream Boundary Weight= 0.5
Weight of XSs Associated with DS Boundary= 0.5
Sediment Output Level= 4
Mass or Volume Output= 0
Output Increment Type= 1
Profile and TS Output Increment= 10
XS Output Flag= 0
XS Output Increment= 10
Disregard all LS=0
Disregard all Conn=0
Disregard all Breaches=0
Disregard all Pumps=0

--- lftfrkrffb.f01 (steady flow) ---

Flow Title=USGS Regression Equation
Program Version=4.00
Number of Profiles= 1
Profile Names=P100yr
River Rch & RM=lftfrkrffb,Main            ,2202.9
     366
River Rch & RM=lftfrkrffb,Main            ,1755.5
     374
River Rch & RM=lftfrkrffb,Main            ,250.1
     407
Boundary for River Rch & Prof#=lftfrkrffb,Main            , 1
Up Type= 0
Dn Type= 3
Dn Slope=0.0725
DSS Import GetInterval= 0
DSS Import GetPeak= 0
DSS Import FillOption= 0

--- lftfrkrffb.g01 (geometry) ---

Geom Title=USGS 3m DEM
Program Version=4.00

River Reach=lftfrkrffb      ,Main
Reach XY= 30
      1628311.03      291450.049     1628417.261      291465.676
     1628537.985      291465.975     1628598.426      291460.935
     1628649.522      291475.242     1628677.775      291502.843
     1628703.279      291512.287     1628730.471      291509.683
     1628803.222      291489.714     1628848.367      291500.923
     1628893.191      291528.802     1628927.785      291536.849
      1629001.91      291525.959     1629110.912      291503.455
     1629314.173      291434.094     1629379.673      291430.701
     1629403.425      291420.388     1629411.229      291405.455
     1629413.691      291343.583     1629433.745      291316.713
     1629667.794       291306.73     1629766.323      291279.539
     1629846.329      291277.733     1629888.492      291282.938
     1630009.374      291272.681      1630044.36      291258.136
     1630109.896      291215.369     1630208.565      291176.151
      1630270.94      291143.863     1630327.868      291079.228

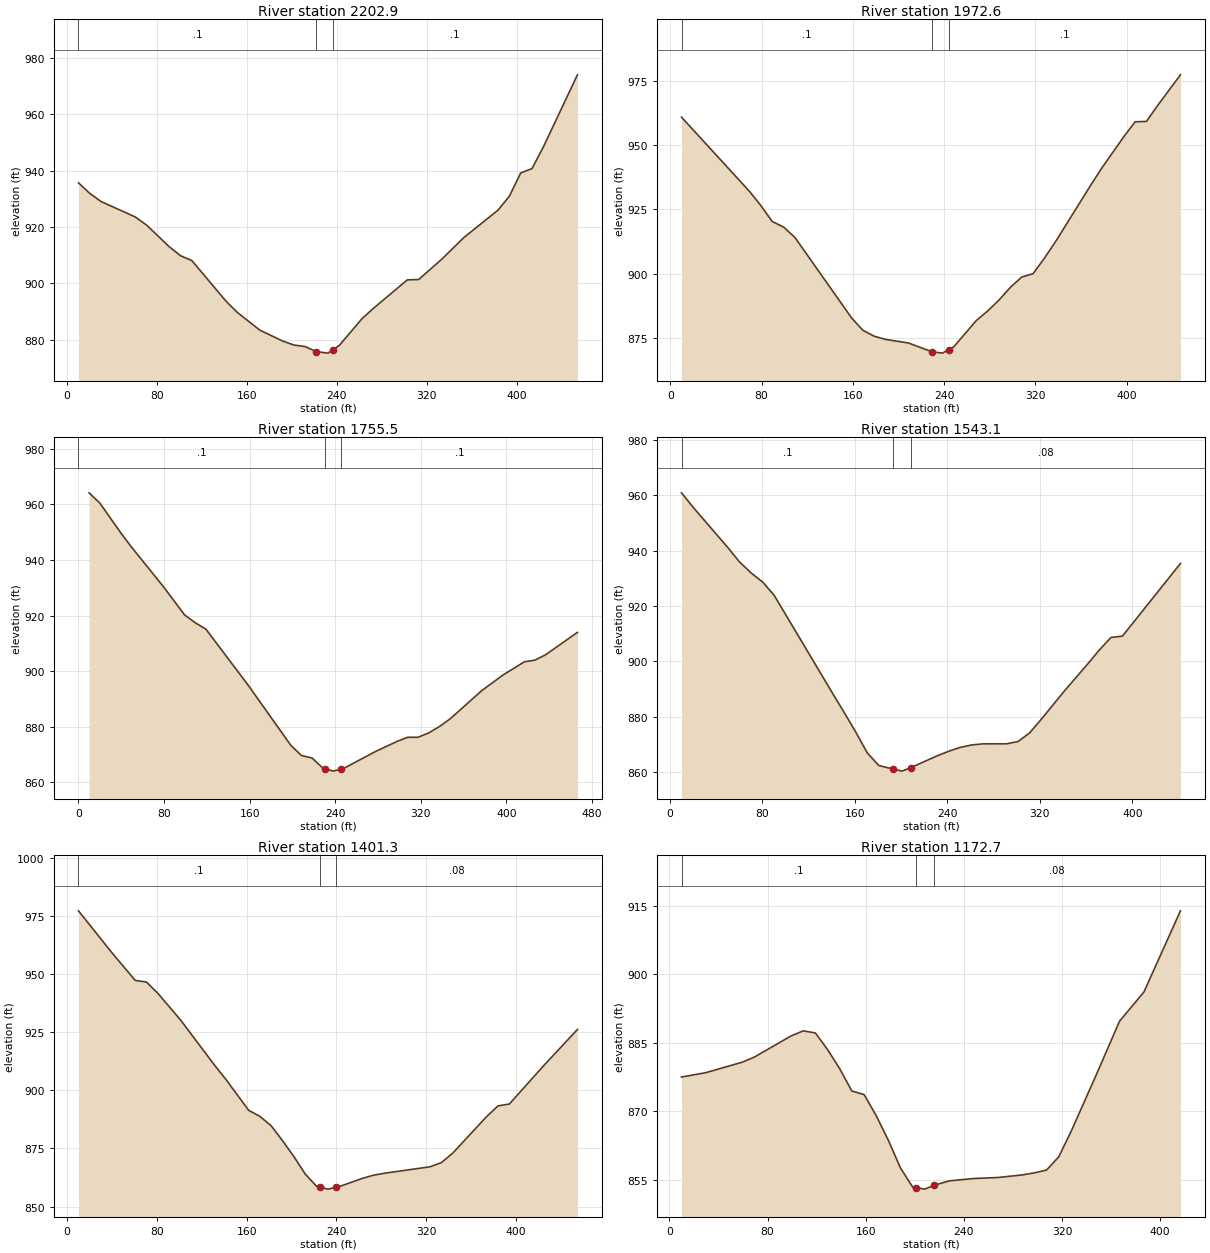
Type RM Length L Ch R = 1 ,2202.9  ,234,230.4,226.7
XS GIS Cut Line= 2
     1628284.656      291675.294     1628354.112      291226.536
#Sta/Elev= 30
    10.1  935.67    20.2  931.91    30.3  929.01    60.5   923.6    70.6  920.72
    90.8  913.04   100.9  909.82     111  908.09   141.3  893.74   151.4  889.72
   171.5  883.42   191.7  879.57   201.8  878.14   211.9  877.59   221.6 875.823
   232.1  875.27   236.6 876.494   242.2  878.01   262.4  887.49   272.5  891.14
   302.7  901.25   312.8  901.37     333  908.45   353.2  916.32   383.5  926.01
   393.6  930.96   403.6  939.17   413.7  940.73   423.8  948.43   454.1  973.98
#Mann= 3 , 0 , 0
    10.1      .1       0   221.6    .045       0   236.6      .1       0
Bank Sta=221.6,236.6
XS Rating Curve= 0 ,0
Exp/Cntr=0.3,0.1

Type RM Length L Ch R = 1 ,1972.6  ,217.2,217.1,217
XS GIS Cut Line= 2
      1628550.18      291702.245     1628547.185      291255.048
#Sta/Elev= 30
     9.9  960.94    69.6  931.99    79.5  926.47    89.4  920.31    99.4  918.13
   109.3   914.1     159  882.74   168.9  877.93   178.9  875.61   188.8  874.39
   208.7  873.01     229 869.635   238.5  869.05     244 870.377   248.4  871.44
   268.3  881.76   278.3  885.48   288.2  889.73   298.1  894.66   308.1  898.68
     318  899.99     328  906.04   337.9   912.6   367.7  933.85   377.6   940.7
   397.5  953.32   407.5  959.15   417.4  959.28   427.3  965.55   447.2  977.43
#Mann= 3 , 0 , 0
     9.9      .1       0     229    .045       0     244      .1       0
Bank Sta=229,244
XS Rating Curve= 0 ,0
Exp/Cntr=0.3,0.1

Type RM Length L Ch R = 1 ,1755.5  ,214.1,212.3,210.5
XS GIS Cut Line= 2
     1628756.809      291734.188     1628741.048      291267.968
#Sta/Elev= 30
     9.9   964.2    19.9  960.54    39.7   949.7    49.6  944.65    79.4  930.43
    99.3   920.2   109.2  917.43   119.1  915.14   158.8  894.86   198.5  873.31
   208.4  869.64   218.4  868.72   228.3  865.16   230.7  864.88   238.2     864
   245.7  864.77   248.1  865.01   277.9   871.1   297.8  874.69   307.7  876.18
   317.6   876.2   327.5  877.77   337.5  880.06   347.4  882.79   377.2  893.04
     397  898.63   416.9  903.37   426.8  903.96   436.7  905.89   466.5  913.95
#Mann= 3 , 0 , 0
       0      .1       0   230.7    .045       0   245.7      .1       0
Bank Sta=230.7,245.7
XS Rating Curve= 0 ,0
Exp/Cntr=0.3,0.1

Type RM Length L Ch R = 1 ,1543.1  ,144,141.8,139.6
XS GIS Cut Line= 2
     1628969.428      291724.206     1628922.512      291284.994
#Sta/Elev= 30
      10  960.82    20.1  955.59    50.2  941.03    60.2   935.9    70.3  931.91
    80.3  928.62    90.3  923.79   140.5  888.67   150.6  881.73   160.6  874.67
   170.7  867.07   180.7   862.5   193.3   861.2   200.8  860.47   208.3  861.71
   230.9  865.93   240.9   867.6     251  869.01     261  869.91     271  870.31
   291.1  870.32   301.2  871.14   311.2  874.26   321.2  879.14   341.3  889.38
   361.4   899.1   371.4  904.09   381.5  908.64   391.5  909.15   441.7  935.35
#Mann= 3 , 0 , 0
      10      .1       0   193.3    .045       0   208.3     .08       0
Bank Sta=193.3,208.3
XS Rating Curve= 0 ,0
Exp/Cntr=0.3,0.1

Type RM Length L Ch R = 1 ,1401.3  ,230.7,228.7,226.6
XS GIS Cut Line= 2
     1629134.502      291730.882     1629042.505       291285.28
#Sta/Elev= 30
    10.1  977.25    40.4  958.93    60.7  947.32    70.8  946.58    80.9  941.73
   101.1  930.29   131.4  910.85   141.6  904.69   161.8  891.44   171.9  888.81
     182  884.71   192.1  878.31   202.2   871.5   212.3  863.98   222.4  858.71
   225.1  858.39   232.6   857.5   240.1  858.31   242.7  858.59   262.9  862.08
     273  863.48   283.1  864.35   323.6  867.12   333.7  868.91   343.8  872.99
   374.1  888.75   384.2  893.31   394.3  894.12   424.7  910.53     455  926.19
#Mann= 3 , 0 , 0
    10.1      .1       0   225.1    .045       0   240.1     .08       0
Bank Sta=225.1,240.1
XS Rating Curve= 0 ,0
Exp/Cntr=0.3,0.1

Type RM Length L Ch R = 1 ,1172.7  ,220.1,213.4,207.1
XS GIS Cut Line= 2
     1629364.718      291630.375     1629242.937      291232.089
#Sta/Elev= 30
     9.9   877.5    29.7  878.46    59.5  880.76    69.4  881.89    99.2   886.5
   109.1  887.61     119  887.15   128.9  883.52   138.8  879.34   148.7  874.45
   158.7  873.67   168.6  869.03   178.5  863.63   188.4  857.58   198.3  853.41
   200.7  853.31   208.2  852.98   215.7  853.82   228.1  854.79   247.9   855.3
   267.7  855.52   287.6  856.09   297.5  856.54   307.4  857.16   317.3  860.04
   327.2   865.5   347.1  877.51   366.9  889.74   386.7   896.1   416.5  913.87
#Mann= 3 , 0 , 0
     9.9      .1       0   200.7    .045       0   215.7     .08       0
Bank Sta=200.7,215.7
XS Rating Curve= 0 ,0
Exp/Cntr=0.3,0.1

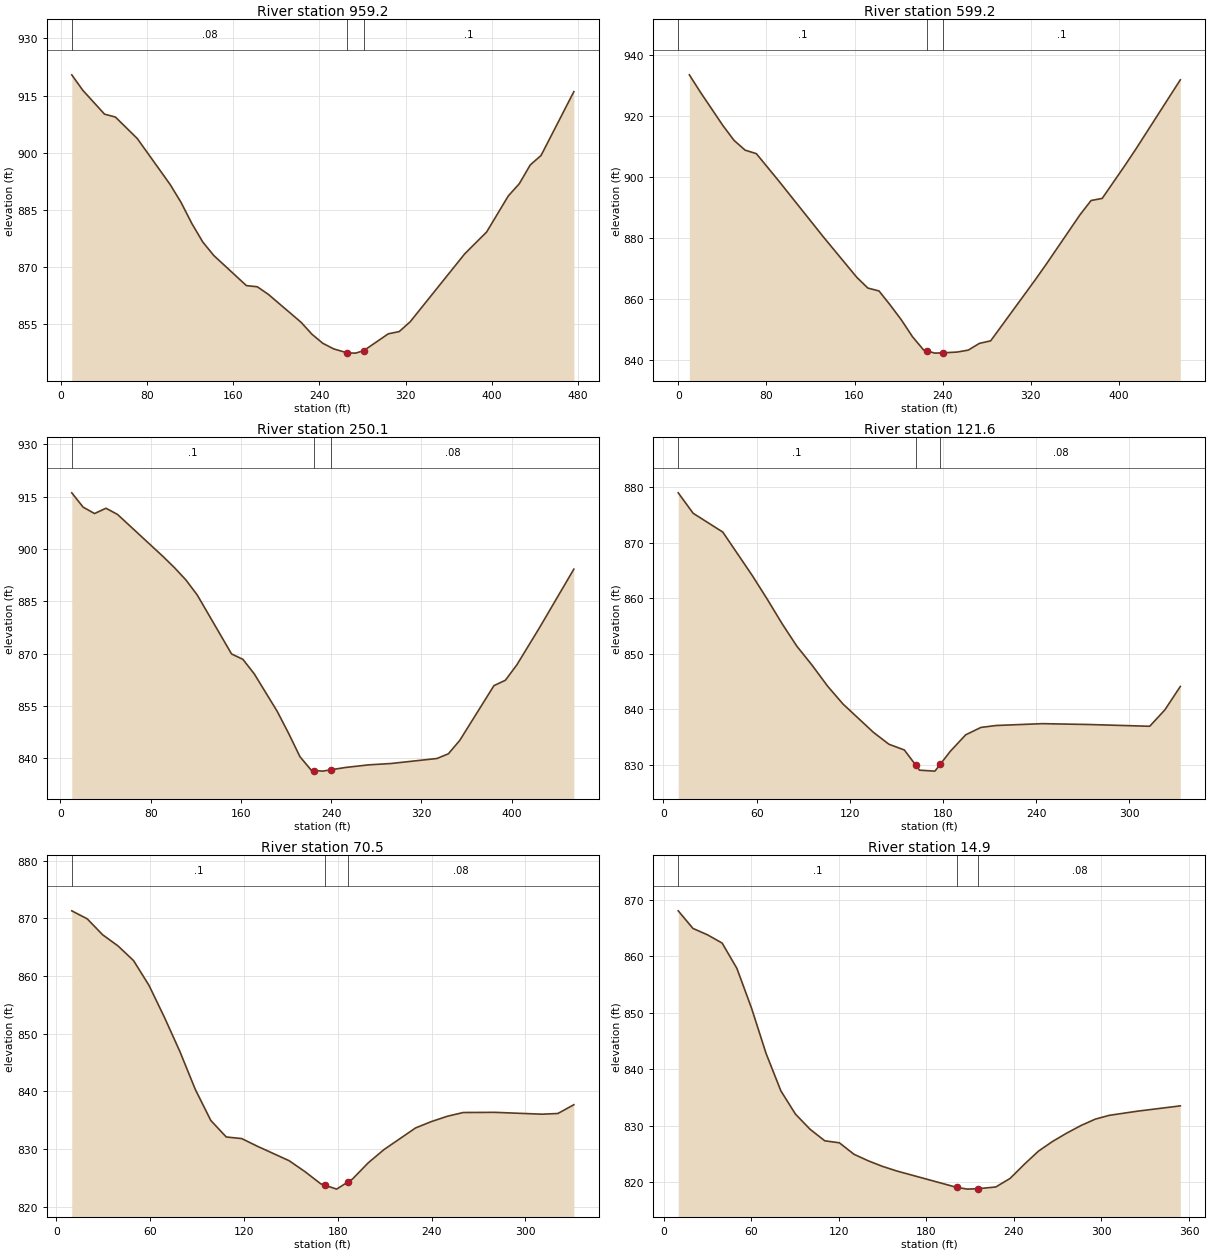
Type RM Length L Ch R = 1 ,959.2   ,348.3,360,371.3
XS GIS Cut Line= 2
     1629581.238      291553.526     1629329.781      291149.238
#Sta/Elev= 30
    10.1  920.46    20.3  916.42    40.5  910.15    50.6  909.39    70.9  903.76
   101.3  891.75   111.4  887.08   121.6  881.45   131.7  876.63   141.8  873.12
   172.2  865.19   182.3  864.89   192.5  862.91   222.9  855.59     233  852.45
   243.1  850.07   253.2   848.6     266  847.54   273.5  847.49     281  848.13
   303.9  852.55     314  853.14   324.2  855.71   374.8  873.52   395.1  879.23
   415.3  888.72   425.5  891.92   435.6  896.82   445.7  899.33   476.1  916.04
#Mann= 3 , 0 , 0
    10.1     .08       0     266    .045       0     281      .1       0
Bank Sta=266,281
XS Rating Curve= 0 ,0
Exp/Cntr=0.3,0.1

Type RM Length L Ch R = 1 ,599.2   ,356.5,349.1,341.8
XS GIS Cut Line= 2
      1629809.13      291505.154     1629770.742      291051.194
#Sta/Elev= 30
    10.1  933.51    20.2  927.78    40.5   916.9    50.6  912.03    60.7  908.81
    70.9  907.66    91.1  898.77   131.6  880.41     162  867.12   172.1  863.58
   182.2  862.64   192.4     858   202.5  853.14   212.6  847.61   222.7  843.27
   225.4     843   232.9  842.25   240.4  842.35   253.1   842.6   263.2  843.24
   273.3  845.45   283.5  846.27     324  866.31   334.1  871.49   364.5  887.58
   374.6  892.29   384.7  892.98     405  903.61   415.1  909.07   455.6  931.87
#Mann= 3 , 0 , 0
       0      .1       0   225.4    .045       0   240.4      .1       0
Bank Sta=225.4,240.4
XS Rating Curve= 0 ,0
Exp/Cntr=0.3,0.1

Type RM Length L Ch R = 1 ,250.1   ,130,128.5,127
XS GIS Cut Line= 2
     1630210.604      291415.557     1630029.386      290998.202
#Sta/Elev= 30
    10.1  916.13    20.2  912.02    30.3  910.19    40.4  911.71    50.6  909.95
      91  897.88   101.1  894.69   111.2  891.19   121.3  886.85   151.7  869.96
   161.8   868.4   171.9  864.21   192.1  853.54   202.2  847.24   212.3  840.52
   222.4  836.61   225.1  836.55   232.6  836.38   240.1  836.79   252.8  837.43
     273  838.17   293.2  838.57   333.7     840   343.8  841.34   353.9  845.18
   384.2  860.88   394.3  862.41   404.4  866.79   424.7  877.55     455  894.26
#Mann= 3 , 0 , 0
    10.1      .1       0   225.1    .045       0   240.1     .08       0
Bank Sta=225.1,240.1
XS Rating Curve= 0 ,0
Exp/Cntr=0.3,0.1

Type RM Length L Ch R = 1 ,121.6   ,50.6,51.1,51.6
XS GIS Cut Line= 3
     1630273.089      291318.933     1630277.082      291233.087
     1630164.284      291013.481
#Sta/Elev= 26
     9.5  879.01    19.1  875.33    38.2  871.94    57.3  864.06    66.8  859.86
    76.4  855.43    85.9  851.38    95.8  847.92   105.7  844.18   115.6  840.97
   135.3  835.84   145.2  833.72   155.1  832.69   162.3 830.016   164.9  829.05
   174.8  828.88   178.3 830.145   184.7  832.45   194.6  835.42   204.4  836.75
   214.3   837.1   243.9  837.43   273.6  837.28   313.1  836.96   322.9  839.93
   332.8  844.13
#Mann= 3 , 0 , 0
     9.5      .1       0   162.3    .045       0   178.3     .08       0
Bank Sta=162.3,178.3
XS Rating Curve= 0 ,0
Exp/Cntr=0.3,0.1

Type RM Length L Ch R = 1 ,70.5    ,52.8,55.5,58.3
XS GIS Cut Line= 3
     1630286.613      291300.995      1630307.74      291184.296
     1630213.173      290994.157
#Sta/Elev= 30
     9.9  871.31    19.8  869.92    29.6  867.17    39.5  865.22    49.4  862.69
    59.3  858.39    69.2  852.83    79.1  846.89    88.9  840.36    98.8  834.98
   108.7  832.11   118.6  831.83   128.7  830.49   148.9     828     159  826.11
   169.2  823.98   171.8  823.75   179.3  823.07   186.8  824.36   189.4  824.81
   199.5  827.63   209.6  829.93   229.8  833.68   239.9  834.78   250.1   835.7
   260.2  836.35   280.4  836.38   310.7  836.06   320.8  836.18     331   837.7
#Mann= 3 , 0 , 0
     9.9      .1       0   171.8    .045       0   186.8     .08       0
Bank Sta=171.8,186.8
XS Rating Curve= 0 ,0
Exp/Cntr=0.3,0.1

Type RM Length L Ch R = 1 ,14.9    ,27.9,14.9,1.9
XS GIS Cut Line= 3
     1630298.044       291292.98     1630352.005      291174.235
     1630268.882      290966.664
#Sta/Elev= 30
      10  868.06    20.1  864.94    30.1  863.81    40.1  862.35    50.2  857.87
    60.2  850.86    70.2  842.82    80.3  836.22    90.3   832.1   100.3  829.42
   110.4  827.37   120.4  827.02   130.4  824.99   140.2  823.83   149.9  822.85
   159.6  822.04   200.7  819.14   208.2  818.82   215.7   818.9   227.6   819.2
   237.4  820.72   247.1  823.21   256.8  825.54   266.5  827.26   276.3  828.75
     286  830.08   295.7   831.2   305.4  831.88   324.9  832.62     354  833.55
#Mann= 3 , 0 , 0
      10      .1       0   200.7    .045       0   215.7     .08       0
Bank Sta=200.7,215.7
XS Rating Curve= 0 ,0
Exp/Cntr=0.3,0.1

Chan Stop Cuts=-1
Use User Specified Reach Order=0